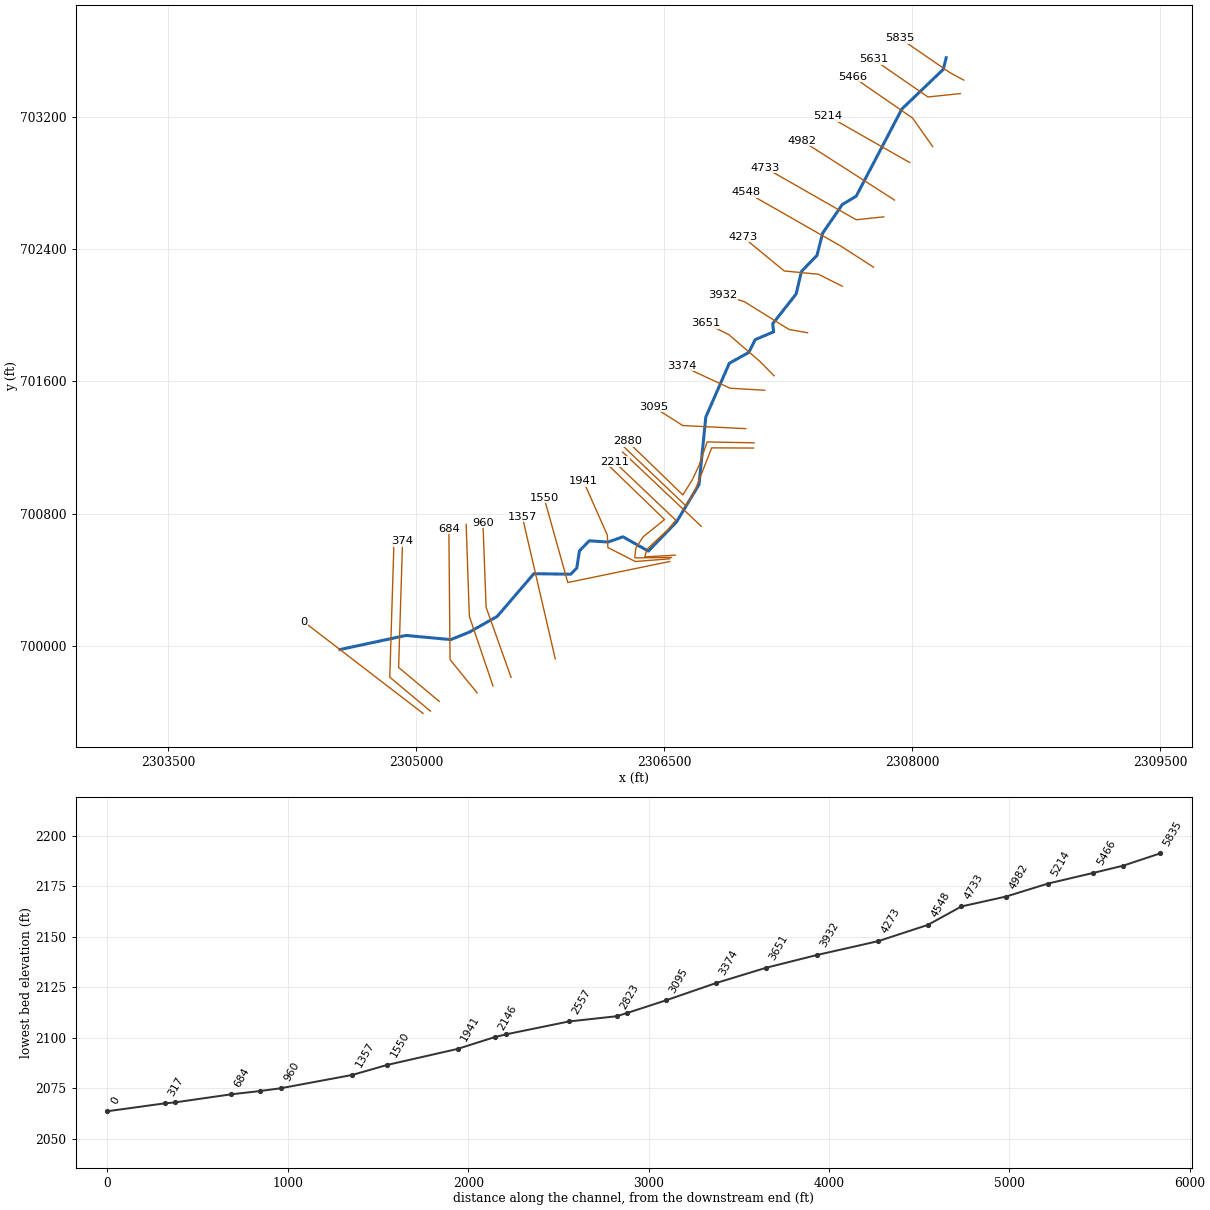
--- POERN.prj (project) ---

Proj Title=POERN
Current Plan=p01
Default Exp/Contr=0,0
English Units
Geom File=g01
Flow File=f01
Plan File=p01
BEGIN DESCRIPTION:
----------MODEL BY WSP USA 2022----------
AFH study
Randolph County, WV
HEC-RAS Version: RAS 6.2
Vertical Datum: NAVD88
Projection: NAD 1983 StatePlane West Virginia S FIPS 4702 (US Feet)
Terrain: 1-meter LIDAR (FEMA Region III 3DEP collected 2016-2018)
Land Use: 2019 NLCD
Hydrologic Method:
WV SIR2010-5033 regression equations
Additional Model Notes:
2 dominant flow path issues; POERN has larger DA than ISNERCK_L (formerly ISNERCK) but lower shifted flows. Applied flows based on raw unfiltered flows.
Another dominant flow path issue with POERNT1. Streamline and XSs US of their confluence were swapped. 1 shared XS between the models.
KWSEL tie-in used for name change with ISNERCK_L
END DESCRIPTION:
DSS Export Rating Curves= 0
DSS Export Rating Curve Sorted= 0
DSS Export Volume Flow Curves= 0
DXF OffsetX= 0
DXF OffsetY= 0
DXF ScaleX= 0
DXF ScaleY= 0

--- POERN.p01 (plan) ---

Plan Title=Floodplain
Program Version=6.20
Short Identifier=Floodplain
Geom File=g01
Flow File=f01
Subcritical Flow
K Sum by GR= 0
Std Step Tol= 0.01
Critical Tol= 0.01
Num of Std Step Trials= 20
Max Error Tol= 0.3
Flow Tol Ratio= 0.001
Split Flow NTrial= 30
Split Flow Tol= 0.02
Split Flow Ratio= 0.02
Log Output Level= 0
Friction Slope Method= 1
Unsteady Friction Slope Method= 2
Unsteady Bridges Friction Slope Method= 1
Parabolic Critical Depth
Global Vel Dist= 0 , 0 , 0
Global Log Level= 0
CheckData=True
Encroach Param=-1 ,0,0, 0
Mapping Interval=1HOUR
Computation Time Step Use Courant=        0
Computation Time Step Use Time Series=    0
Computation Time Step Count To Double=0
Computation Time Step Max Doubling=0
Computation Time Step Max Halving=0
Computation Time Step Residence Courant=0
Run HTab= 0
Run UNet= 0
Run Sediment= 0
Run PostProcess= 0
Run WQNet= 0
Run RASMapper=-1
UNET Theta= 0
UNET Theta Warmup= 0
UNET ZTol= 0
UNET ZSATol= 0
UNET MxIter= 0
UNET Max Iter WO Improvement= 0
UNET MaxInSteps= 0
UNET DtIC= 0
UNET DtMin= 0
UNET MaxCRTS= 0
UNET WFStab= 0
UNET SFStab= 0
UNET WFX= 1
UNET SFX= 1
UNET Gravity=32.174
UNET 1D Methodology=Finite Difference
UNET DSS MLevel= 1
UNET Pardiso=0
UNET DZMax Abort= 0
UNET Use Existing IB Tables= 0
UNET Froude Reduction=False
UNET Froude Limit= 0
UNET Froude Power= 0
UNET D1 Cores= 0
UNET WindReference=Eulerian
UNET WindDragFormulation=Hsu (1988)
UNET D2 Coriolis=0
UNET D2 Cores= 0
UNET D2 Theta= 1
UNET D2 Theta Warmup= 1
UNET D2 Z Tol= 0.01
UNET D2 Volume Tol= 0.01
UNET D2 Max Iterations= 20
UNET D2 Equation= 0
UNET D2 RampUpFraction=0.1
UNET D2 TimeSlices= 1
UNET D2 Turbulence Formulation=Non-Conservative (original)
UNET D2 Eddy Viscosity=0.3
UNET D2 Transverse Eddy Viscosity=0.1
UNET D2 Smagorinsky Mixing=0
UNET D2 BCVolumeCheck=0
UNET D2 Cores=0
UNET D2 SolverType=PARDISO (Direct)
UNET D2 Minimum Iterations= 2147483647
UNET D2 Maximum Iterations= 2147483647
UNET D2 Restart Number= 10
UNET D2 Relaxation Coeff=1.3
UNET D2 SOR Precondition Iterations= 10
UNET D2 ILUT Maximum Fill= 8
UNET D2 ILUT Tolerance=1E-08
UNET D1D2 MaxIter= 0
UNET D1D2 ZTol=0.01
UNET D1D2 QTol=0.1
UNET D1D2 MinQTol=1
Write IC File= 0
Write IC File at Fixed DateTime=0
Write IC File at Sim End=0
Echo Input=False
Echo Parameters=False
Echo Output=False
Write Detailed= 0
HDF Write Warmup=0
HDF Write Time Slices=0
HDF Flush=0
HDF Compression= 1
HDF Chunk Size= 1
HDF Spatial Parts= 1
HDF Use Max Rows=0
HDF Fixed Rows= 1
Calibration Method= 0
Calibration Iterations= 20
Calibration Max Change=0.05
Calibration Tolerance=0.2
Calibration Maximum=1.5
Calibration Minimum=0.5
Calibration Optimization Method= 1
WQ AD Non Conservative
WQ ULTIMATE=-1
WQ Max Comp Step=1HOUR
WQ Output Interval=15MIN
WQ Output Selected Increments= 0
WQ Output face flow=0
WQ Output face velocity=0
WQ Output face area=0
WQ Output face dispersion=0
WQ Output cell volume=0
WQ Output cell surface area=0
WQ Output cell continuity=0
WQ Output cumulative cell continuity=0
WQ Output face conc=0
WQ Output face dconc_dx=0
WQ Output face courant=0
WQ Output face peclet=0
WQ Output face adv mass=0
WQ Output face disp mass=0
WQ Output cell mass=0
WQ Output cell source sink temp=0
WQ Output nsm pathways=0
WQ Output nsm derived pathways=0
WQ Create Restart=0
WQ Fixed Restart=0
WQ System Summary=0
WQ Write To DSS=0
Sorting and Armoring Iterations= 10
XS Update Threshold= 0.02
Bed Roughness Predictor= 0
Hydraulics Update Threshold= 0.02
Energy Slope Method= 1
Volume Change Method= 1
Sediment Retention Method= 0
Sediment TS Multiplier= 1
Warm Up Method= 0
XS Weighting Method= 0
Number of US Weighted Cross Sections= 1
Number of DS Weighted Cross Sections= 1
Upstream XS Weight=0
Main XS Weight=1
Downstream XS Weight=0
Number of DS XS's Weighted with US Boundary= 1
Upstream Boundary Weight= 1
Weight of XSs Associated with US Boundary= 0
Number of US XS's Weighted with DS Boundary= 1
Downstream Boundary Weight= 0.5
Weight of XSs Associated with DS Boundary= 0.5
Percentile Method= 0
Sediment Output Level= 3
Mass or Volume Output= 0
Output Increment Type= 1
Profile and TS Output Increment= 1
Transport Output Increment 1
XS Output Flag= 0
XS Output Increment= 10
Read HDF5 Sediment Hotstart= 0
Sediment Hotstart Type= 0
Write Gradation File= 0
Read Gradation Hotstart= 0
Write HDF5 File= 1
Write Binary Output= 1
Write DSS Sediment File= 0
DSS Sediment Output Type= 1
SV Curve= 0
Specific Gage Flag= 0
Subcell Erosion Methods= 0
Subcell Deposition Methods= 0
Advection Scheme= 1
Matrix Solver= 0
Implicit Weighting Factor= 1
Maximum Outer Loop Convergence Iterations= 5
Convergence Maximum Absolute= 0.001
Convergence RMSE= 0.0001
Grain Fractions Max Abs Error= 0.001
Max Subgrid Regions= 1
Max Subgrid Length Scale= 3.402823E+38
Initial Layer Thickness= 3.402823E+38
Min Layer Thickness= 3.402823E+38
Max Layer Thickness= 3.402823E+38
Number of Layers= 5

--- POERN.f01 (steady flow) ---

Flow Title=Flow
Program Version=6.20
Number of Profiles= 1
Profile Names=P100yr
River Rch & RM=POERN,Main            ,5835
     345
River Rch & RM=POERN,Main            ,1941
     392
River Rch & RM=POERN,Main            ,1357
     688
River Rch & RM=POERN,Main            ,0
     982
Boundary for River Rch & Prof#=POERN,Main            , 1
Up Type= 0
Dn Type= 1
Dn Known WS=2067.5
DSS Import GetInterval= 0
DSS Import GetPeak= 0
DSS Import FillOption= 0

--- POERN.g01 (geometry) ---

Geom Title=Geometry
Program Version=6.20

River Reach=POERN           ,Main
Reach XY= 30
2308204.63599999      703557.7872308187.04700005703487.322000012
2307936.58100002703247.3710000072307660.19100003 702719.59300001
     2307576.858702670.2870000152307457.47899999702496.151999995
2307423.47300005702362.3299999982307329.27143501702264.851879537
2307297.17100003702128.388999999     2307155.244701948.268000022
2307161.75399998701900.0910000212307049.77500001 701852.34800002
     2307011.146701775.0910000062306893.26899999 701709.65200001
2306751.16399999701384.8990000192306709.93099999700976.045000002
2306573.64599998700749.4829999952306403.50800002700573.268000007
2306250.29600003700659.6390000132306159.58400005700627.955000013
2306046.30300002700635.7680000072305986.84100001700574.569999993
2305970.78200001700471.2710000132305933.88900003700433.511000007
2305711.30500002700436.6090000122305489.34200004 700178.26000002
2305322.50200002700084.028999999     2305208.799700037.890000016
2304937.75999999 700063.201000022304538.51789737699977.772661865

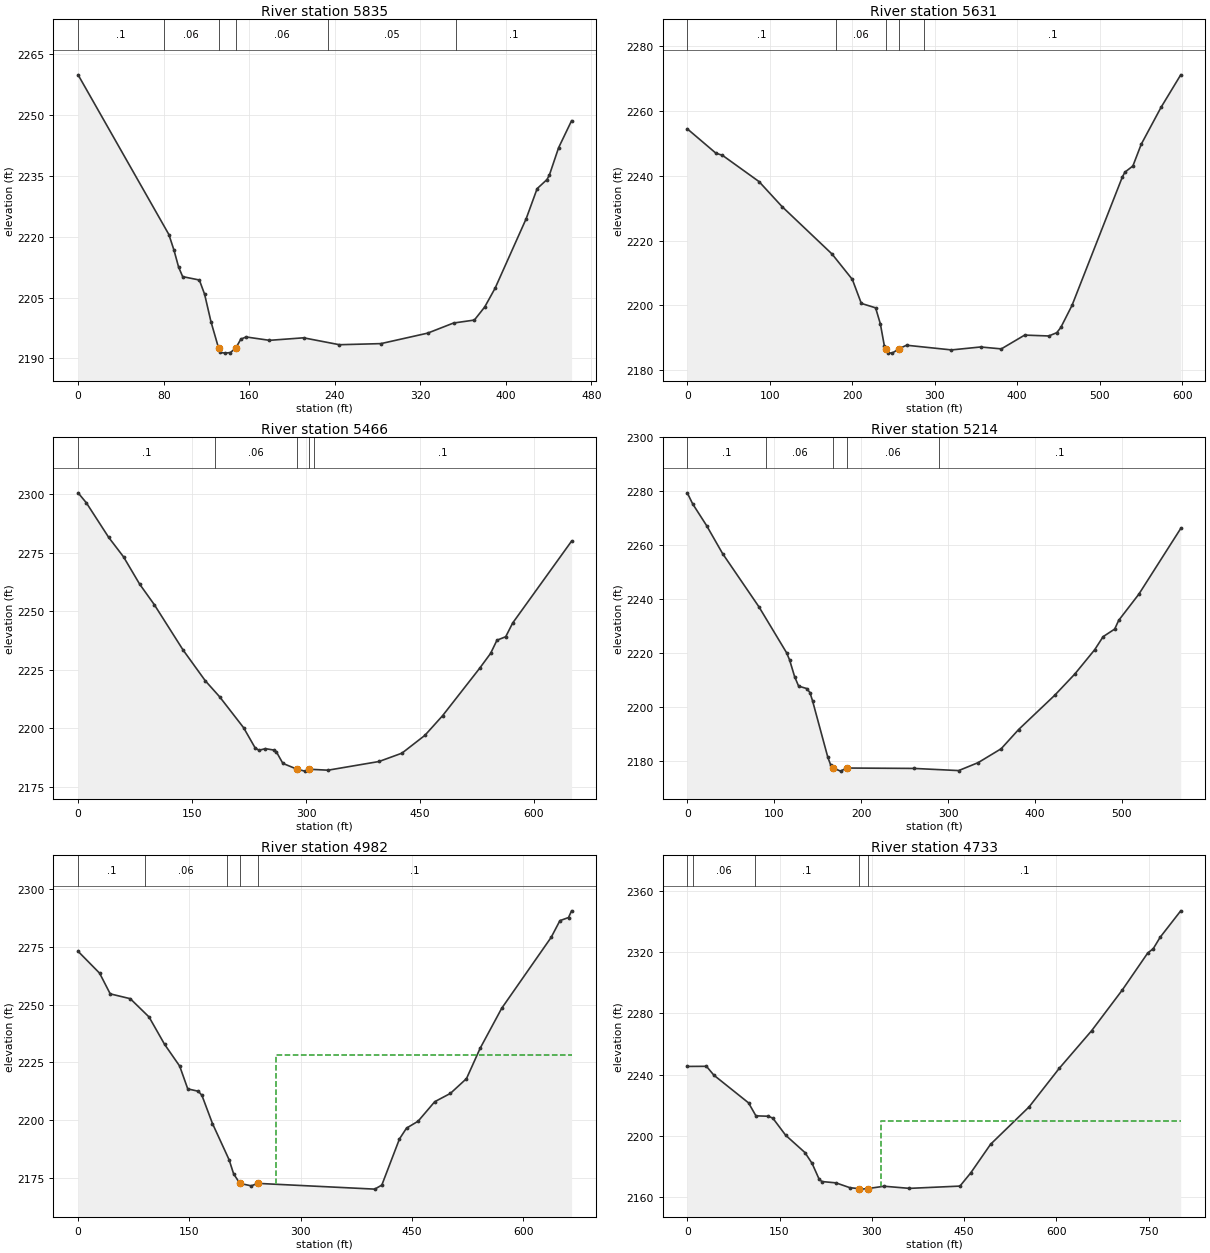
Type RM Length L Ch R = 1 ,5835    ,203,203.6,203.1
XS GIS Cut Line= 3
2308310.84453916703422.2818812782308228.79728211703466.587400087
2307925.22243101703674.987433003
#Sta/Elev= 30
       0 2259.82    84.9 2220.51    89.7 2216.64      94 2212.49    97.8 2210.14
   113.4 2209.31   118.3 2205.82   124.3 2199.02  131.38 2192.56     133 2191.48
   137.7 2191.31   142.5 2191.46   147.4 2192.54   152.2 2194.75   157.1 2195.29
     179 2194.46   210.9 2195.08   244.4 2193.38   283.2 2193.65   326.9 2196.23
   351.1 2198.72   370.6 2199.45   380.3 2202.68     390  2207.3   419.1 2224.43
   429.3  2231.8   438.5 2234.04   440.8 2235.18   449.4 2241.89   461.5 2248.52
#Mann= 6, -1 ,  0
       0     0.1       0      80    0.06       0  131.38   0.045       0
   147.4    0.06       0  233.25    0.05       0  353.25     0.1       0
Bank Sta=131.38,147.4
XS Rating Curve= 0 ,0
Exp/Cntr=0.3,0.1

Type RM Length L Ch R = 1 ,5631    ,166,165.5,165.9
XS GIS Cut Line= 3
2308290.69097751703340.7694971162308094.45773934 703320.37167432
2307764.44613365703548.073481911
#Sta/Elev= 30
       0 2254.55    34.7 2247.03    42.7 2246.36      87 2238.25   114.8 2230.55
   175.5 2215.87   200.1 2208.03     211 2200.62   228.3 2199.25   234.1 2194.27
   238.9 2187.51  240.352186.616   243.8 2185.35   248.4 2185.26  257.262186.682
   265.8  2187.7   320.3 2186.25   355.6 2187.16   380.7 2186.57     409 2190.83
   438.2 2190.56   447.9 2191.57   452.8 2193.18   466.4 2200.01   527.3  2239.6
   530.5 2241.16   540.2 2243.08   550.3 2249.78   574.3 2261.18   598.2 2271.23
#Mann= 5, -1 ,  0
       0     0.1       0     180    0.06       0  240.35   0.045       0
  257.26    0.06       0  287.29     0.1       0
Bank Sta=240.35,257.26
XS Rating Curve= 0 ,0
Exp/Cntr=0.3,0.1

Type RM Length L Ch R = 1 ,5466    ,250.7,251.4,252.2
XS GIS Cut Line= 3
2308122.89870376 703020.306696442308001.46876332703192.605936252
2307640.46083228703442.029597695
#Sta/Elev= 30
       0 2300.68    10.9  2296.4    40.2 2281.67    59.8 2273.31    81.1  2261.6
   100.2 2252.92   138.1 2233.52   167.4 2220.33   186.3 2213.47   217.9 2200.23
   232.9  2191.7     238 2190.59   246.6 2191.28   258.1 2190.66     261 2189.92
   269.6 2184.97  287.792182.554   298.4 2181.67   304.1 2182.48     329 2182.07
   396.2 2185.79   426.3 2189.35   456.5 2196.96   479.8 2205.37   528.5 2225.61
     543 2232.01   551.4 2237.66   562.9 2239.14   572.1 2245.02   649.6 2280.02
#Mann= 5, -1 ,  0
       0     0.1       0     180    0.06       0  287.79   0.045       0
   304.1    0.06       0  310.79     0.1       0
Bank Sta=287.79,304.1
XS Rating Curve= 0 ,0
Exp/Cntr=0.3,0.1

Type RM Length L Ch R = 1 ,5214    ,232.5,232.4,232.2
XS GIS Cut Line= 2
2307983.44890842702923.985222886 2307490.1406849703204.927574395
#Sta/Elev= 30
       0  2279.5     6.2 2275.41    22.2 2267.38    40.6 2257.01    82.5 2237.24
   114.2 2220.28   117.7  2217.6   123.5 2211.39   128.1 2207.88   137.3    2207
   141.1 2205.52   144.1 2202.46   161.7 2181.52   164.9 2178.73  168.092177.527
   176.3 2176.39   183.3 2177.54   261.1 2177.39   312.2 2176.59   334.7 2179.55
   361.1 2184.68   381.2 2191.81   422.7 2204.49   445.7 2212.32   468.7 2221.37
   478.4 2226.21   491.7 2229.02   496.3 2232.24   519.5 2241.95   567.7 2266.31
#Mann= 5, -1 ,  0
       0     0.1       0      90    0.06       0  168.09   0.045       0
   183.3    0.06       0     290     0.1       0
Bank Sta=168.09,183.3
XS Rating Curve= 0 ,0
Exp/Cntr=0.3,0.1

Type RM Length L Ch R = 1 ,4982    ,248.1,248.5,247
XS GIS Cut Line= 2
 2307892.5751364702696.3928813092307333.01284329703055.759867204
#Sta/Elev= 30
       0 2273.14      29 2263.65    43.3 2254.68    70.3 2252.59    95.6 2244.66
   116.6 2232.76   136.9 2223.34   147.8 2213.45   162.1 2212.42   166.9 2210.62
   181.1 2198.41   203.5 2182.71   209.6 2176.58     218 2172.46   233.4 2171.38
  241.932172.458   399.8 2169.96   409.3 2171.72   433.1 2191.75   442.6 2196.43
   458.2 2199.43   480.6 2207.89   501.7 2211.49   523.4 2217.91   541.8 2231.07
   570.9 2248.45   637.5  2279.2   649.3 2286.45   660.9  2287.8     665 2290.71
#Mann= 5, -1 ,  0
       0     0.1       0      90    0.06       0     200     0.1       0
     218   0.045       0  241.93     0.1       0
#XS Ineff= 2 , 0
                          266.86         2228.07
Permanent Ineff=
       F       F
Bank Sta=218,241.93
XS Rating Curve= 0 ,0
Exp/Cntr=0.3,0.1

Type RM Length L Ch R = 1 ,4733    ,185.3,185.8,185.1
XS GIS Cut Line= 3
 2307827.1966152702595.2419331732307660.31249435 702577.51972565
2307109.44721049702892.088909193
#Sta/Elev= 30
       0 2245.32    31.2  2245.4    43.3 2239.58    99.6 2221.48   111.6 2212.98
   131.9 2212.72   139.2 2211.43   159.9  2200.3   191.3 2188.96   202.9 2181.87
     214 2171.86   218.6    2170   241.7 2169.12   264.4 2165.96  278.49 2165.37
   283.1 2165.02   293.7  2165.4     320 2166.91   361.2 2165.52   443.3 2167.01
   460.9  2175.7   493.1 2194.39   555.7 2218.86   604.5 2243.97   657.3 2268.68
   707.2 2295.35   748.4 2319.47   757.6 2322.44   768.7 2329.84   802.2 2347.15
#Mann= 5, -1 ,  0
       0     0.1       0      10    0.06       0     110     0.1       0
  278.49   0.045       0   293.7     0.1       0
#XS Ineff= 2 , 0
                          315.52         2209.31
Permanent Ineff=
       F       F
Bank Sta=278.49,293.7
XS Rating Curve= 0 ,0
Exp/Cntr=0.3,0.1

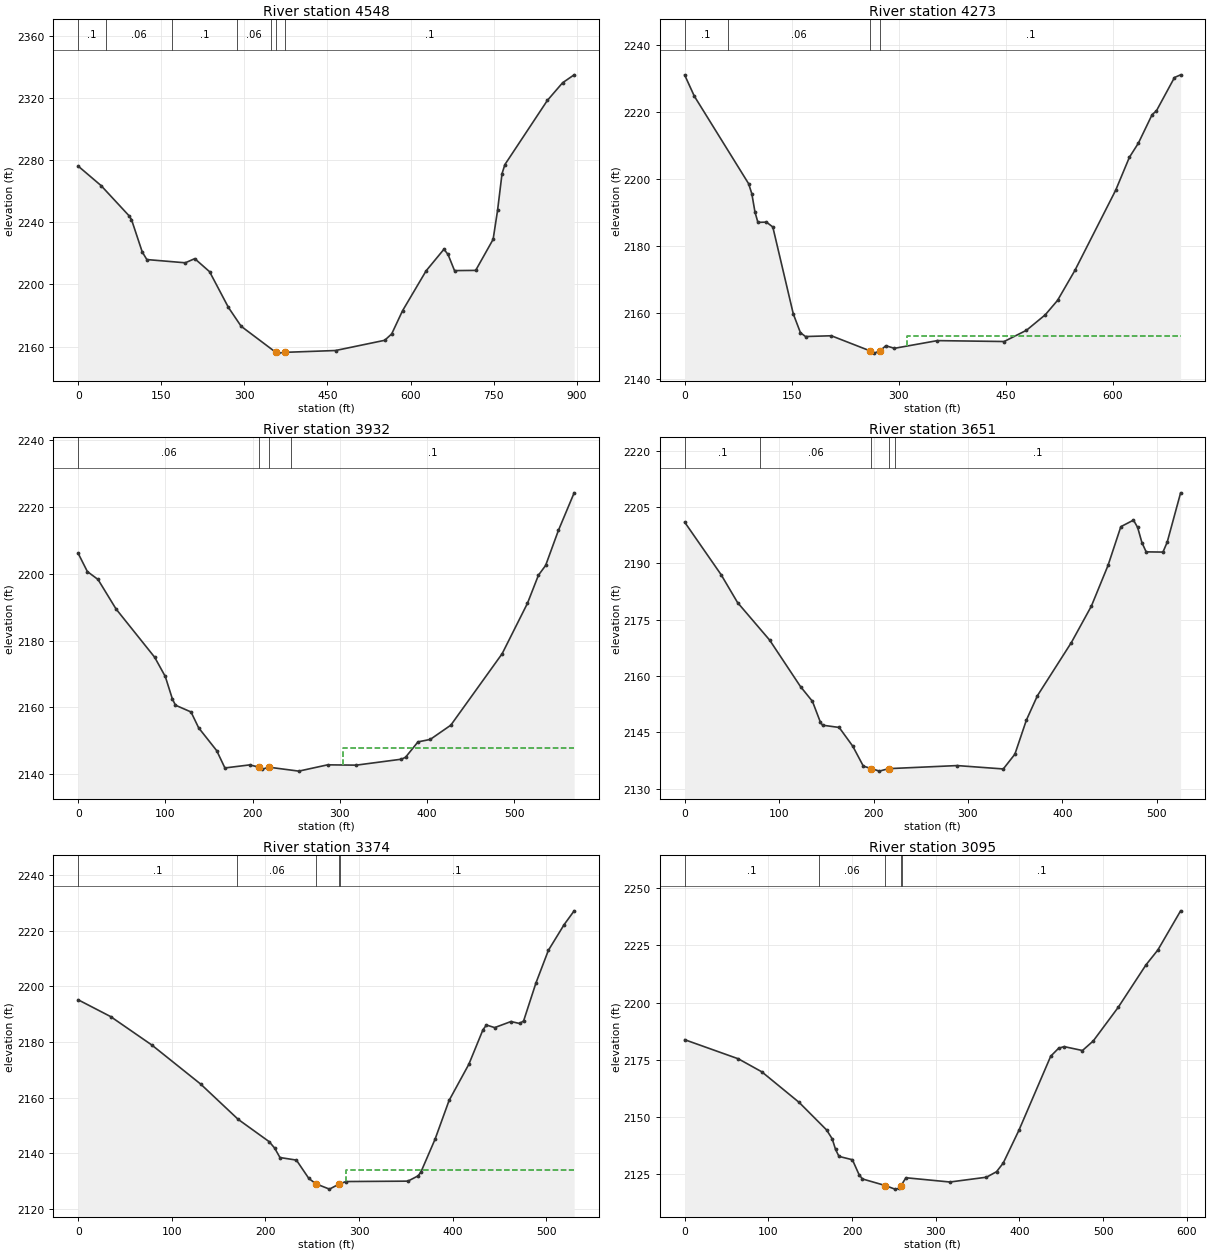
Type RM Length L Ch R = 1 ,4548    ,270,274.4,276.5
XS GIS Cut Line= 3
2307765.06415938702290.8502065092307565.68932474702419.336211055
 2306994.1481321702745.720199614
#Sta/Elev= 30
       0 2276.05    41.2 2263.58    91.5 2244.27    96.2 2241.73   115.6  2220.9
   123.9 2216.02   193.3 2213.94   210.4  2216.6   237.2 2208.21   271.2 2185.26
   294.2 2173.14   356.9 2156.36   359.9 2155.89   372.5 2156.39   464.6 2157.57
   553.4 2164.14     566 2168.26   585.6 2183.16   628.1 2208.76   660.3 2222.65
   667.7 2219.29   679.4 2208.92   717.6 2209.06   749.1    2229   757.1 2247.55
   765.2 2271.23   770.3 2277.02     847 2318.27   874.6 2329.66   895.4 2334.73
#Mann= 7, -1 ,  0
       0     0.1       0      50    0.06       0     170     0.1       0
  287.19    0.06       0  347.19     0.1       0   356.9   0.045       0
   372.5     0.1       0
Bank Sta=356.9,372.5
XS Rating Curve= 0 ,0
Exp/Cntr=0.3,0.1

Type RM Length L Ch R = 1 ,4273    ,344.2,341.3,337.9
XS GIS Cut Line= 4
2307576.27448687702175.5266925882307431.26113152 702248.18285911
2307225.30398974702267.8013705812306973.69149519702474.792095198
#Sta/Elev= 30
       0 2230.99    13.5 2224.68    89.6  2198.5    94.1 2195.49    98.5 2190.03
   102.6 2186.95   114.6 2187.02   123.5 2185.56   152.2 2159.57   162.2 2153.97
   169.3 2152.82   205.5 2153.05  259.772148.534   265.7 2147.86   273.8 2148.57
   281.8 2150.07   293.9  2149.3   354.1  2151.6   447.6 2151.33   478.9 2154.69
   505.2 2159.31   522.4 2163.61   546.7 2172.56   603.9 2196.55   623.1 2206.39
   635.7 2210.62     655 2219.17   660.9 2220.25   686.3 2230.25   694.9 2231.05
#Mann= 4, -1 ,  0
       0     0.1       0      60    0.06       0  259.77   0.045       0
   273.8     0.1       0
#XS Ineff= 2 , 0
                          311.55         2152.99
Permanent Ineff=
       F       F
Bank Sta=259.77,273.8
XS Rating Curve= 0 ,0
Exp/Cntr=0.3,0.1

Type RM Length L Ch R = 1 ,3932    ,279.9,281.4,280.1
XS GIS Cut Line= 4
2307366.49764925701893.930109232  2307253.927146701914.166192634
2306983.37683487702082.6967008152306852.78853757702120.060435905
#Sta/Elev= 30
       0 2206.05    10.5 2200.62    22.7 2198.26    43.4 2189.44    87.7 2175.01
    99.9 2169.25   108.1 2162.49   111.6 2160.67   129.4 2158.65   138.2  2153.9
   158.9 2147.08   168.3 2141.91   196.6 2142.82  206.862142.198   210.8 2141.47
   218.4 2142.15   253.1 2140.96   286.1 2142.84   319.1 2142.75   370.9 2144.53
   375.6 2145.12   389.8  2149.7   403.9 2150.44   427.5  2154.7   486.4 2176.07
   515.4 2191.12     528 2199.52   536.3 2202.47   550.9  2212.9     569 2224.16
#Mann= 4, -1 ,  0
       0    0.06       0  206.86   0.045       0   218.4    0.06       0
  244.37     0.1       0
#XS Ineff= 2 , 0
                          303.76         2147.98
Permanent Ineff=
       F       F
Bank Sta=206.86,218.4
XS Rating Curve= 0 ,0
Exp/Cntr=0.3,0.1

Type RM Length L Ch R = 1 ,3651    ,272.2,277.1,279.3
XS GIS Cut Line= 5
2307164.04346092701633.801115951 2307082.3164724701716.200643942
2307077.76267399701721.0940908942306889.36831323701883.340450614
2306751.43166814701951.395405057
#Sta/Elev= 30
       0 2200.98    38.6 2186.98      56 2179.56      90 2169.55   122.7 2157.15
   135.3 2153.24   143.8 2147.63     146 2146.88   163.6 2146.28     178 2141.29
   189.2 2135.97   197.7 2135.32   206.2 2134.64  215.92  2135.3   288.5 2136.12
   337.4 2135.22   349.7 2139.16   361.9 2148.26   373.6 2154.76   409.5 2168.91
   430.7 2178.62   448.3 2189.44   461.9 2199.78   475.3 2201.53   479.7 2199.57
   484.2 2195.55   488.7 2193.07   506.5 2193.01     511 2195.66   525.2  2208.8
#Mann= 5, -1 ,  0
       0     0.1       0      80    0.06       0   197.7   0.045       0
  215.92    0.06       0  222.74     0.1       0
Bank Sta=197.7,215.92
XS Rating Curve= 0 ,0
Exp/Cntr=0.3,0.1

Type RM Length L Ch R = 1 ,3374    ,275.2,278.8,282.5
XS GIS Cut Line= 3
2307106.75407029 701546.30440284 2306897.2224908701558.635847045
2306607.21501183701693.674912152
#Sta/Elev= 30
       0 2195.17    34.6 2189.15    78.7  2178.9   130.8 2164.87   170.9 2152.17
     204 2144.15   209.9 2141.82   215.5 2138.45   233.1 2137.52   246.3 2130.95
   253.8 2129.01   268.4 2127.08  278.882128.937   286.1 2129.81   352.2 2129.95
   363.1 2131.86   366.1 2133.23   381.2 2145.03   396.2 2158.98   417.3 2171.99
   432.4 2184.41   436.1 2186.11   444.9 2185.18   462.3 2187.36   471.5 2186.66
   475.8 2187.58     489 2201.25   502.3 2212.99   519.1 2222.22   529.8 2227.18
#Mann= 5, -1 ,  0
       0     0.1       0     170    0.06       0   253.8   0.045       0
  278.88    0.06       0  279.89     0.1       0
#XS Ineff= 2 , 0
                          286.47         2133.81
Permanent Ineff=
       F       F
Bank Sta=253.8,278.88
XS Rating Curve= 0 ,0
Exp/Cntr=0.3,0.1

Type RM Length L Ch R = 1 ,3095    ,195.7,215.2,224.9
XS GIS Cut Line= 3
2306992.30684515   701314.1071862306611.62128156701332.762263932
2306433.26090936701446.262419285
#Sta/Elev= 30
       0 2183.78    64.2 2175.41    92.2 2169.73   136.7  2156.4   169.6 2144.33
   176.3 2140.45   180.3 2135.81   184.4 2132.78   200.4 2131.32   208.4 2124.79
   212.4 2122.93   239.8 2120.04   251.2 2118.48   256.4 2118.78  258.432119.983
   264.4 2123.45     317 2121.59   360.6 2123.69   372.6 2126.08   380.6 2129.85
   399.5 2144.29   437.4 2176.58   446.9 2180.07   453.5 2180.75   475.3 2179.05
   488.2 2183.23     518 2197.91   551.2 2216.47   565.4 2222.98   592.6 2240.09
#Mann= 5, -1 ,  0
       0     0.1       0     160    0.06       0   239.8   0.045       0
  258.43    0.06       0     260     0.1       0
Bank Sta=239.8,258.43
XS Rating Curve= 0 ,0
Exp/Cntr=0.3,0.1

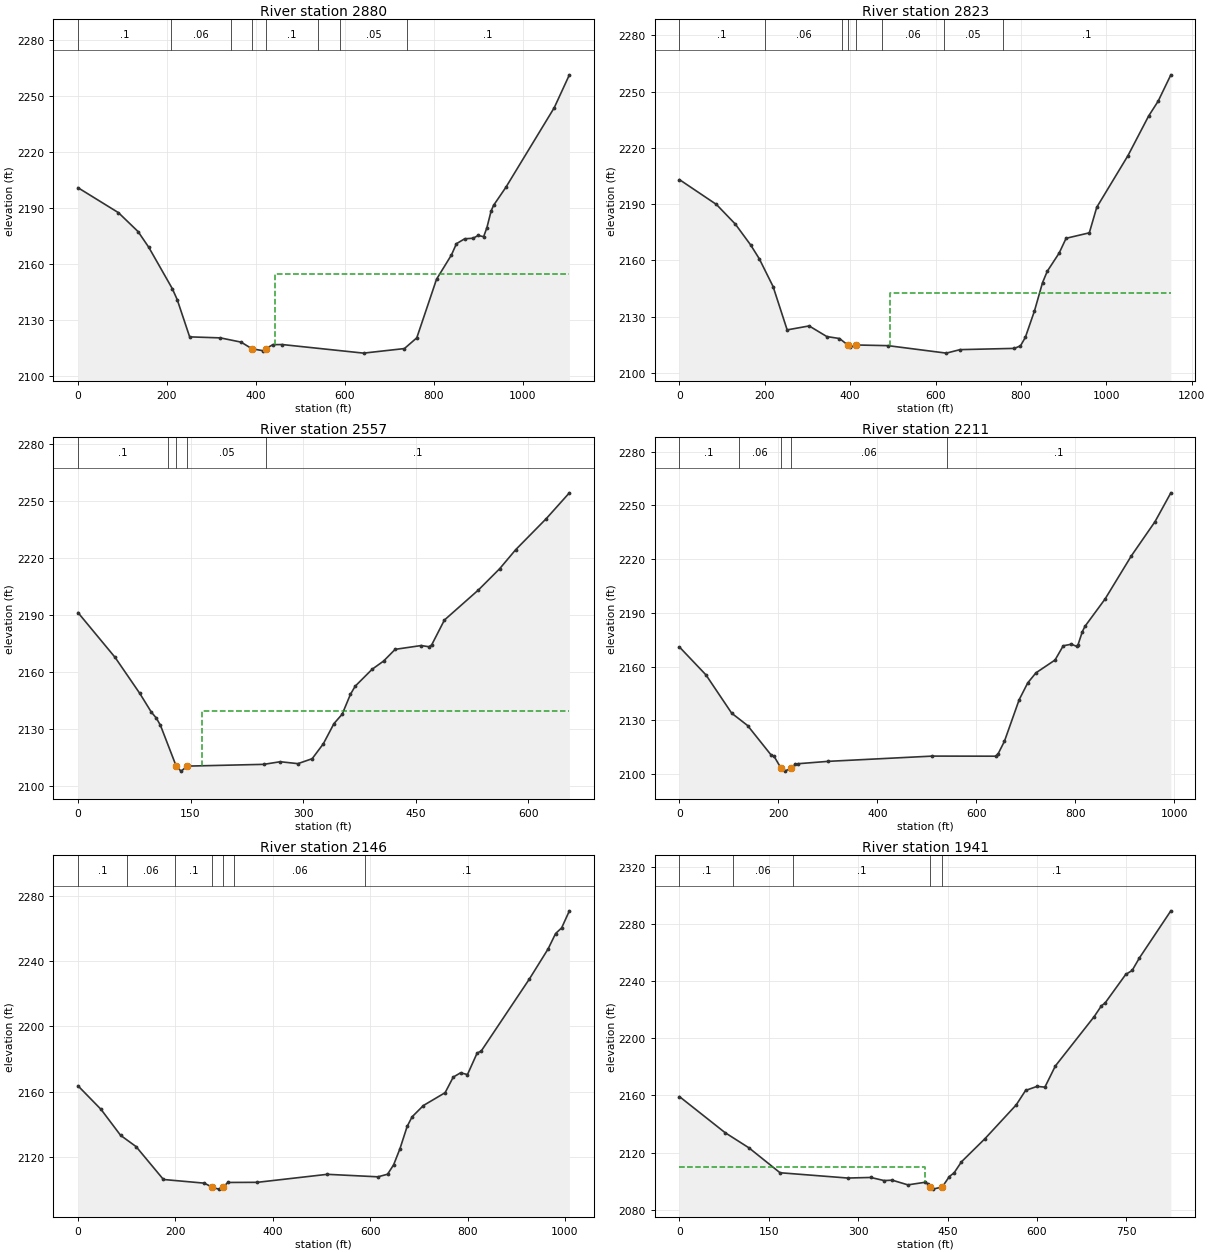
Type RM Length L Ch R = 1 ,2880    ,67.6,57,56.2
BEGIN DESCRIPTION:
Structure XS 3
END DESCRIPTION:
XS GIS Cut Line= 6
2307043.16774712701228.2290098842306758.93898285701233.612130419
2306709.41427393701089.3445000732306669.57918197701005.367819723
2306612.51810429700912.778146516  2306277.688007 701236.84200274
#Sta/Elev= 30
       0 2200.99      91 2187.58     135 2177.46     159 2169.05     212 2146.81
     223 2140.95     251 2120.94   320.1 2120.39   366.7 2118.11  390.892114.562
   415.7 2113.51  421.892114.542   437.9 2116.74   458.9 2116.82   641.9 2112.21
   733.7 2114.66   761.5 2120.41   805.9 2151.86   839.5 2164.94   850.6 2170.93
   869.2 2173.58     888 2173.87   899.4 2175.34   911.8 2174.71   919.2  2179.6
   928.5 2188.44   934.1 2191.52   961.9 2201.26  1070.5 2243.94  1104.5 2261.57
#Mann= 8, -1 ,  0
       0     0.1       0     210    0.06       0  344.28     0.1       0
  390.89   0.045       0  421.89     0.1       0  539.82    0.06       0
  589.82    0.05       0  738.58     0.1       0
#XS Ineff= 2 , 0
                          443.85         2154.89
Permanent Ineff=
       F       F
Bank Sta=390.89,421.89
XS Rating Curve= 0 ,0
Exp/Cntr=0.3,0.1

Type RM Length L Ch R = 1 ,2823    ,276.9,265.2,252.5
BEGIN DESCRIPTION:
Structure XS 2
END DESCRIPTION:
XS GIS Cut Line= 6
2307038.96887757701196.6514547172306786.64535086701197.795779101
2306689.37777821700950.0495499312306656.19237107700888.256033187
2306631.01723462700847.0603553572306258.30877307701201.313407207
#Sta/Elev= 30
       0 2203.08    86.7 2189.83   130.9 2179.38   166.6 2168.33   186.8 2160.99
   219.3 2146.13   252.3 2123.02   303.8 2125.13   345.2 2119.47   374.9 2118.42
  394.672114.911   400.5 2113.69   412.4 2114.99   488.8 2114.62   625.1 2110.64
   657.4  2112.5   784.7 2113.17   798.9 2114.54   810.2 2119.03   831.6  2133.1
   850.5 2148.18   861.6 2154.26   889.4 2163.93   905.7 2171.82   960.1 2174.73
   977.5 2188.33  1050.7 2215.89  1098.9 2236.91  1121.4  2244.9  1151.1 2258.91
#Mann= 8, -1 ,  0
       0     0.1       0     200    0.06       0  380.56     0.1       0
  394.67   0.045       0   412.4     0.1       0  475.04    0.06       0
  618.63    0.05       0  756.91     0.1       0
#XS Ineff= 2 , 0
                          493.86         2142.48
Permanent Ineff=
       F       F
Bank Sta=394.67,412.4
XS Rating Curve= 0 ,0
Exp/Cntr=0.3,0.1

Type RM Length L Ch R = 1 ,2557    ,356.3,346.2,334.8
BEGIN DESCRIPTION:
Structure XS 4
END DESCRIPTION:
XS GIS Cut Line= 2
2306724.05058774700722.9271242132306248.17649683701172.546092867
#Sta/Elev= 30
       0  2191.5    49.4 2167.93    82.4 2148.92    97.7 2139.11   104.4 2135.96
   109.9 2132.12  130.89 2110.64   137.3 2108.04   145.8 2110.68   247.5 2111.61
   269.5 2112.99     293 2111.98     312 2114.58   326.9 2122.45     341 2133.04
     352 2138.03     363 2148.47   369.3 2152.74     392  2161.7   407.1 2165.96
   422.6 2172.15   457.1 2174.14   467.6 2173.53   471.2 2174.47   488.2 2187.57
   533.5  2203.4   561.8 2214.58   583.1 2224.58     624    2241   654.7 2254.54
#Mann= 5, -1 ,  0
       0     0.1       0     120    0.05       0  130.89   0.045       0
   145.8    0.05       0     250     0.1       0
#XS Ineff= 2 , 0
                          165.78         2139.45
Permanent Ineff=
       F       F
Bank Sta=130.89,145.8
XS Rating Curve= 0 ,0
Exp/Cntr=0.3,0.1

Type RM Length L Ch R = 1 ,2211    ,64.8,65.4,63.2
BEGIN DESCRIPTION:
Structure XS 3
END DESCRIPTION:
XS GIS Cut Line= 6
2306565.65669559700548.5842051912306381.38640782700538.381921004
2306396.32840542700585.4173938312306523.51515771700704.588853505
2306569.76052332700760.2142135712306198.51564152 701112.75327148
#Sta/Elev= 30
       0 2170.99    53.6 2155.41   105.6 2134.03   137.7 2127.15   184.6 2110.91
   191.4 2109.87205.48342103.251   212.3  2101.7225.29342103.199     234 2105.53
   239.4 2105.83   300.7 2107.16   511.1 2110.09   639.2 2110.04   644.1 2111.45
   656.7 2118.36   686.5 2141.58   703.8 2150.95   720.4 2156.57     759 2163.73
   775.5 2171.66   792.1 2172.55   802.5 2171.34   805.3 2172.11   814.1 2179.52
   819.3 2182.47     860 2197.75   913.4 2221.96     961 2240.96     993 2257.05
#Mann= 5, -1 ,  0
       0     0.1       0     120    0.06       0205.4834   0.045       0
225.2934    0.06       0  540.99     0.1       0
Bank Sta=205.4834,225.2934
XS Rating Curve= 0 ,0
Exp/Cntr=0.3,0.1

Type RM Length L Ch R = 1 ,2146    ,201,205.1,211.8
BEGIN DESCRIPTION:
Structure XS 2
END DESCRIPTION:
XS GIS Cut Line= 6
 2306543.6702945700534.7565194842306321.58550007700532.231281524
 2306327.1782972 700589.668560872306371.75053523700659.433803007
2306501.59140254700764.0816662132306156.74428813701097.762501445
#Sta/Elev= 30
       0 2163.62    47.5  2149.1    87.5 2133.25   119.3 2126.35   175.5 2106.18
   259.2 2103.94275.31722101.547   288.7 2100.27298.7498 2101.68   307.7 2104.36
   368.3 2104.44   512.1 2109.35     616 2107.82   635.8 2109.41   648.2 2115.16
   661.3 2125.09     676  2138.7   686.2 2144.62   709.4 2151.53     754  2159.4
   770.7 2168.96   785.7 2171.57   799.9 2170.51   819.7 2183.67   828.2 2184.96
   927.2 2229.17   965.5 2247.53   980.9 2256.97   993.3 2260.43  1009.2 2270.89
#Mann= 7, -1 ,  0
       0     0.1       0     100    0.06       0     200     0.1       0
275.3172   0.045       0298.7498     0.1       0  319.81    0.06       0
  589.36     0.1       0
Bank Sta=275.3172,298.7498
XS Rating Curve= 0 ,0
Exp/Cntr=0.3,0.1

Type RM Length L Ch R = 1 ,1941    ,387.3,391,392.5
BEGIN DESCRIPTION:
Structure XS 1
END DESCRIPTION:
XS GIS Cut Line= 5
2306532.41658857700526.6075446642306324.39842286700510.343939399
2306158.87169067700594.6852772312306155.49348423700670.234552461
2306011.65755211700994.371864278
#Sta/Elev= 30
       0 2159.16    76.5 2133.96   116.6 2123.32   168.8  2105.9   282.3  2102.2
   321.1  2102.6   343.6 2100.42   357.1  2100.7   383.4 2097.42   412.9 2099.27
   416.9 2098.27420.3396 2095.89     425 2094.44 440.9092095.896     453 2103.25
     461 2105.87   473.3 2113.56   512.7 2129.71   565.2 2153.37   580.9 2163.46
   600.2  2166.3   613.3 2165.76   630.8 2180.52   696.1 2215.13   708.2 2222.67
   714.3 2224.59     749 2244.61   759.7 2247.35   771.8 2256.04   824.7 2289.07
#Mann= 5, -1 ,  0
       0     0.1       0      90    0.06       0     190     0.1       0
420.3396   0.045       0 440.909     0.1       0
#XS Ineff= 2 , 0
           412.5 2110.21
Permanent Ineff=
       F       F
Bank Sta=420.3396,440.909
XS Rating Curve= 0 ,0
Exp/Cntr=0.3,0.1

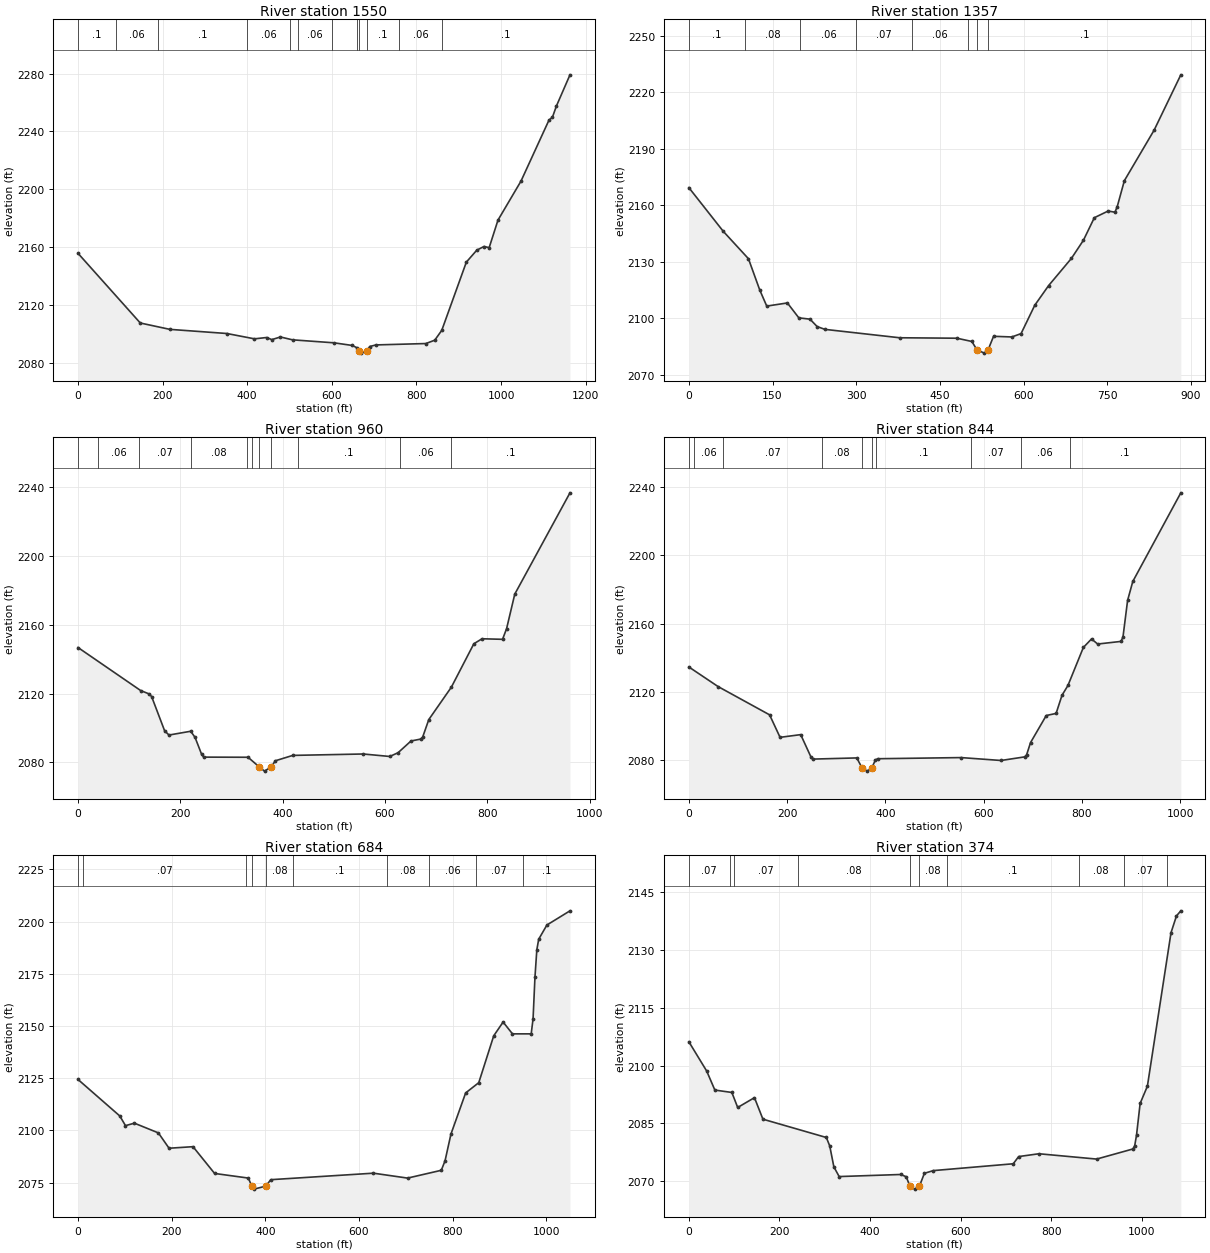
Type RM Length L Ch R = 1 ,1550    ,187.7,192.7,187.7
XS GIS Cut Line= 3
2306532.76669394700510.5392235832305916.37435144700383.218403204
2305772.60628465700897.130670733
#Sta/Elev= 30
       0 2155.56   147.2 2107.34   217.1 2102.94   351.9 2100.07   417.2 2096.38
   445.8  2097.3   458.1 2095.84   478.5 2097.67   507.1 2095.69   605.1 2093.63
   648.1 2091.81   660.4 2090.08664.92772087.914   668.8 2086.49682.83762087.832
   689.6 2091.07   704.4 2092.17   822.3 2093.12   843.3 2095.44   859.9 2102.25
     918 2149.47   942.7 2157.74   959.6 2160.28     972 2159.52   992.8 2178.55
  1047.2 2205.54  1113.3 2247.72  1121.6 2249.82    1131 2257.55    1163  2279.1
#Mann= 12, -1 ,  0
       0     0.1       0      90    0.06       0     190     0.1       0
     400    0.06       0     500     0.1       0     520    0.06       0
     600    0.08       0   659.4     0.1       0664.9277   0.045       0
682.8376     0.1       0   759.4    0.06       0   859.4     0.1       0
Bank Sta=664.9277,682.8376
XS Rating Curve= 0 ,0
Exp/Cntr=0.3,0.1

Type RM Length L Ch R = 1 ,1357    ,391.9,397.2,392.6
XS GIS Cut Line= 2
2305840.69495883699921.1740424912305641.75699505700780.117956723
#Sta/Elev= 30
       0 2169.45    61.6 2146.26   106.8 2131.69   127.1 2115.05   139.6 2106.53
   176.6  2108.2   197.1 2100.28   217.1 2099.59   229.9 2095.66   243.8 2094.17
   377.7 2089.71   480.4 2089.47   507.2 2087.74   516.4 2083.26   529.7 2081.55
  536.292083.307   546.1 2090.48   578.9 2090.14   595.4 2091.92     620    2107
   644.6 2117.35   685.7 2131.89   707.2 2141.52   726.7 2153.47   751.4 2157.01
   763.7  2156.4   767.8  2159.4   780.5 2173.12   833.9 2199.99   881.7 2229.35
#Mann= 8, -1 ,  0
       0     0.1       0     100    0.08       0     200    0.06       0
     300    0.07       0     400    0.06       0     500     0.1       0
   516.4   0.045       0  536.29     0.1       0
Bank Sta=516.4,536.29
XS Rating Curve= 0 ,0
Exp/Cntr(USF)=0,0
Exp/Cntr=0.3,0.1

Type RM Length L Ch R = 1 ,960     ,116.3,116.2,116.5
XS GIS Cut Line= 3
2305573.29929386699809.6497249892305422.47051086700233.530615149
2305403.27884847700744.944209374
#Sta/Elev= 30
       0 2146.88   122.6 2121.81   139.6  2119.8   143.9 2118.32   169.3 2098.42
   177.8 2095.95   220.3 2098.15   228.8 2094.58   241.6 2084.75   245.7  2083.1
   332.4 2083.02   354.4 2077.37   364.6 2074.95   377.4 2077.37   385.9 2080.99
   419.8  2084.1   557.6 2084.92   609.4 2083.48   625.7 2085.67   650.9 2092.48
   669.7 2093.59   673.7 2094.71   685.7 2104.94   729.8 2123.79   773.8 2149.07
   789.8 2151.97   829.9 2151.65   837.8 2157.87   853.8 2177.96   961.7 2236.89
#Mann= 11, -1 ,  0
       0     0.1       0      40    0.06       0     120    0.07       0
     220    0.08       0     330    0.07       0     340    0.08       0
   354.4   0.045       0   377.4    0.08       0     430     0.1       0
  629.92    0.06       0  729.92     0.1       0
Bank Sta=354.4,377.4
XS Rating Curve= 0 ,0
Exp/Cntr(USF)=0,0
Exp/Cntr=0.3,0.1

Type RM Length L Ch R = 1 ,844     ,161.8,159.2,151.8
XS GIS Cut Line= 3
2305464.07845099699757.6397998162305321.05115677700178.920193717
2305301.85949438700734.776269003
#Sta/Elev= 30
       0 2134.64    59.5 2123.14   164.3 2106.56   185.6 2093.37   227.6 2094.96
   248.7 2081.71     253 2080.62   341.7  2081.3   352.8 2075.28   362.8 2073.56
   371.7 2075.17   379.7 2080.12   384.3 2080.83   554.1  2081.5   635.3  2079.8
   683.3 2081.91   687.3 2083.12   695.3 2090.29   727.3 2106.17   747.3 2107.39
   759.3 2118.01   771.4 2123.78   802.8 2146.08   819.4 2151.06   831.9 2148.08
   879.4 2149.62   883.4 2152.19   892.8 2173.66   903.4 2184.78  1001.1 2236.74
#Mann= 10, -1 ,  0
       0     0.1       0      10    0.06       0      70    0.07       0
     270    0.08       0   352.8   0.045       0   371.7    0.08       0
     380     0.1       0   574.9    0.07       0   674.9    0.06       0
   774.9     0.1       0
Bank Sta=352.8,371.7
XS Rating Curve= 0 ,0
Exp/Cntr(USF)=0,0
Exp/Cntr=0.3,0.1

Type RM Length L Ch R = 1 ,684     ,311.1,310.9,309.5
BEGIN DESCRIPTION:
Structure XS 4
END DESCRIPTION:
XS GIS Cut Line= 3
2305368.15878368699715.6828281332305204.32751938699916.961238552
2305197.30617948700708.032200433
#Sta/Elev= 30
       0 2124.41    89.2 2106.95   101.4 2102.32   120.4  2103.5   171.6 2098.85
   194.4 2091.51   245.6 2092.25   291.7 2079.44   363.7 2077.23  371.022073.457
   375.7 2071.94   400.9 2073.37   411.7 2076.46   630.9 2079.57   703.8 2077.22
   775.8 2080.95   783.8 2085.49   796.4 2098.27   827.8 2117.97   855.8 2122.88
   887.8 2145.32   907.8 2151.89   927.8 2146.24   967.8 2146.24   971.8  2153.5
   975.8 2173.25   979.8 2186.46   983.8 2191.52  1001.3 2198.32  1050.6 2205.11
#Mann= 10, -1 ,  0
       0     0.1       0      10    0.07       0  359.53    0.08       0
  371.02   0.045       0   400.9    0.08       0  459.53     0.1       0
  659.53    0.08       0  749.53    0.06       0  849.53    0.07       0
  949.53     0.1       0
Bank Sta=371.02,400.9
XS Rating Curve= 0 ,0
Exp/Cntr(USF)=0,0
Exp/Cntr=0.3,0.1

Type RM Length L Ch R = 1 ,374     ,54.4,56,54.3
BEGIN DESCRIPTION:
Structure XS 3
END DESCRIPTION:
XS GIS Cut Line= 4
2305138.93662173699664.3902396992304893.17825667  699869.5365208
2304916.06588084700593.714570088 2304911.3325693700634.651768627
#Sta/Elev= 30
       0 2106.19    39.4 2098.58    57.4 2093.65    94.9 2093.03   107.8 2089.13
   144.8 2091.68   163.5 2086.09   303.5 2081.34     311 2079.13   320.1 2073.71
   331.8  2071.2   467.8 2071.74   479.9 2071.14   487.9  2068.7   498.5 2067.94
   508.9 2068.69   519.9 2072.05   539.8 2072.75     716 2074.52     728 2076.39
   772.7 2077.12   900.1 2075.74   980.1 2078.36   984.1 2079.19   988.1 2081.93
   996.1 2090.18  1012.1 2094.65  1064.3 2134.51  1076.3 2138.85  1085.9 2140.17
#Mann= 10, -1 ,  0
       0    0.07       0      90    0.06       0     100    0.07       0
     240    0.08       0   487.9   0.045       0   508.9    0.08       0
  570.13     0.1       0  860.13    0.08       0  960.13    0.07       0
 1054.67     0.1       0
Bank Sta=487.9,508.9
XS Rating Curve= 0 ,0
Exp/Cntr(USF)=0,0
Exp/Cntr=0.3,0.1

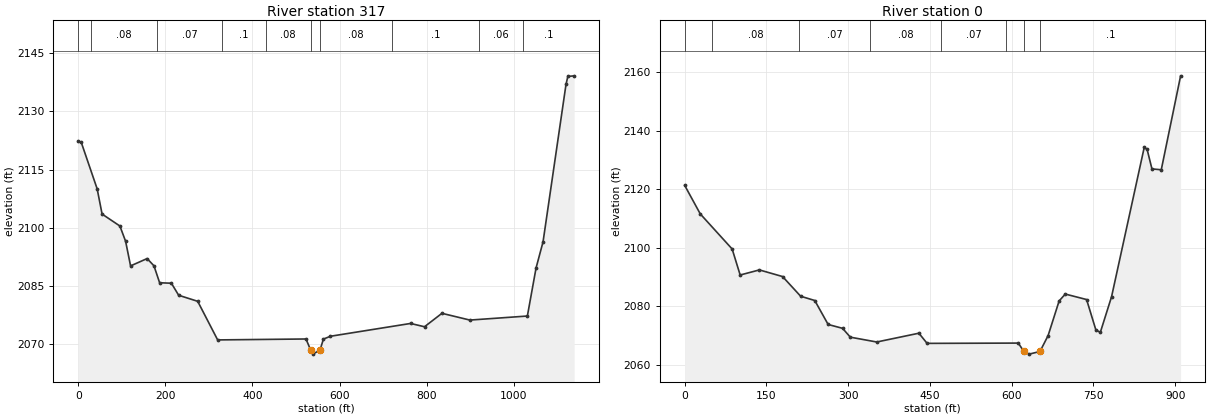
Type RM Length L Ch R = 1 ,317     ,307.5,317.5,333
BEGIN DESCRIPTION:
Structure XS 2
END DESCRIPTION:
XS GIS Cut Line= 4
2305085.64026917699605.3887743412304839.88190411699810.535055442
2304864.09021799700590.1820726062304854.07414761700627.157202011
#Sta/Elev= 30
       0 2122.28     7.1 2121.98    43.5 2110.04    54.8 2103.55    95.7 2100.47
   108.8 2096.54   120.2  2090.2   158.2 2092.09   173.9 2090.22   186.9 2085.86
   213.9 2085.74   230.6 2082.64   274.3 2081.08   320.1 2071.14   522.9 2071.38
  533.59 2068.53   538.9 2067.48  555.152068.548   562.9 2071.35   578.9 2072.08
     763 2075.38     795 2074.53     835 2077.99   899.1 2076.25  1031.1 2077.29
  1051.1 2089.68  1067.1  2096.4  1119.8 2136.93    1124 2138.99  1138.5 2139.15
#Mann= 10, -1 ,  0
       0     0.1       0      30    0.08       0     180    0.07       0
  330.13     0.1       0  430.13    0.08       0  533.59   0.045       0
  555.15    0.08       0  720.13     0.1       0  920.13    0.06       0
 1020.13     0.1       0
Bank Sta=533.59,555.15
XS Rating Curve= 0 ,0
Exp/Cntr(USF)=0,0
Exp/Cntr=0.3,0.1

Type RM Length L Ch R = 1 ,0       ,285.2,288.1,285.5
XS GIS Cut Line= 2
2305040.90855832699591.7251013272304319.45363373700146.106253908
#Sta/Elev= 30
       0 2121.34    28.6 2111.57    87.1 2099.56   101.8 2090.66   137.1  2092.4
   179.6 2090.13   212.8 2083.39   238.7 2081.93   263.2 2073.73   289.7 2072.41
   303.9 2069.38   352.4 2067.73   429.7 2070.74   444.8 2067.26     612 2067.36
  622.392064.503     632 2063.58   651.9 2064.49   666.8 2069.94     687 2081.78
   698.3 2084.14   737.4 2082.26   754.6 2071.75   762.7  2071.1   783.2 2083.23
   843.1  2134.3   848.4 2133.67   857.3 2126.97   874.4 2126.68   909.9 2158.83
#Mann= 8, -1 ,  0
       0    0.07       0      50    0.08       0     210    0.07       0
     340    0.08       0     470    0.07       0     590     0.1       0
  622.39   0.045       0   651.9     0.1       0
Bank Sta=622.39,651.9
XS Rating Curve= 0 ,0
Exp/Cntr=0.3,0.1
LCMann Table=0

Chan Stop Cuts=-1
Use User Specified Reach Order=0
Composite Channel Slope=5